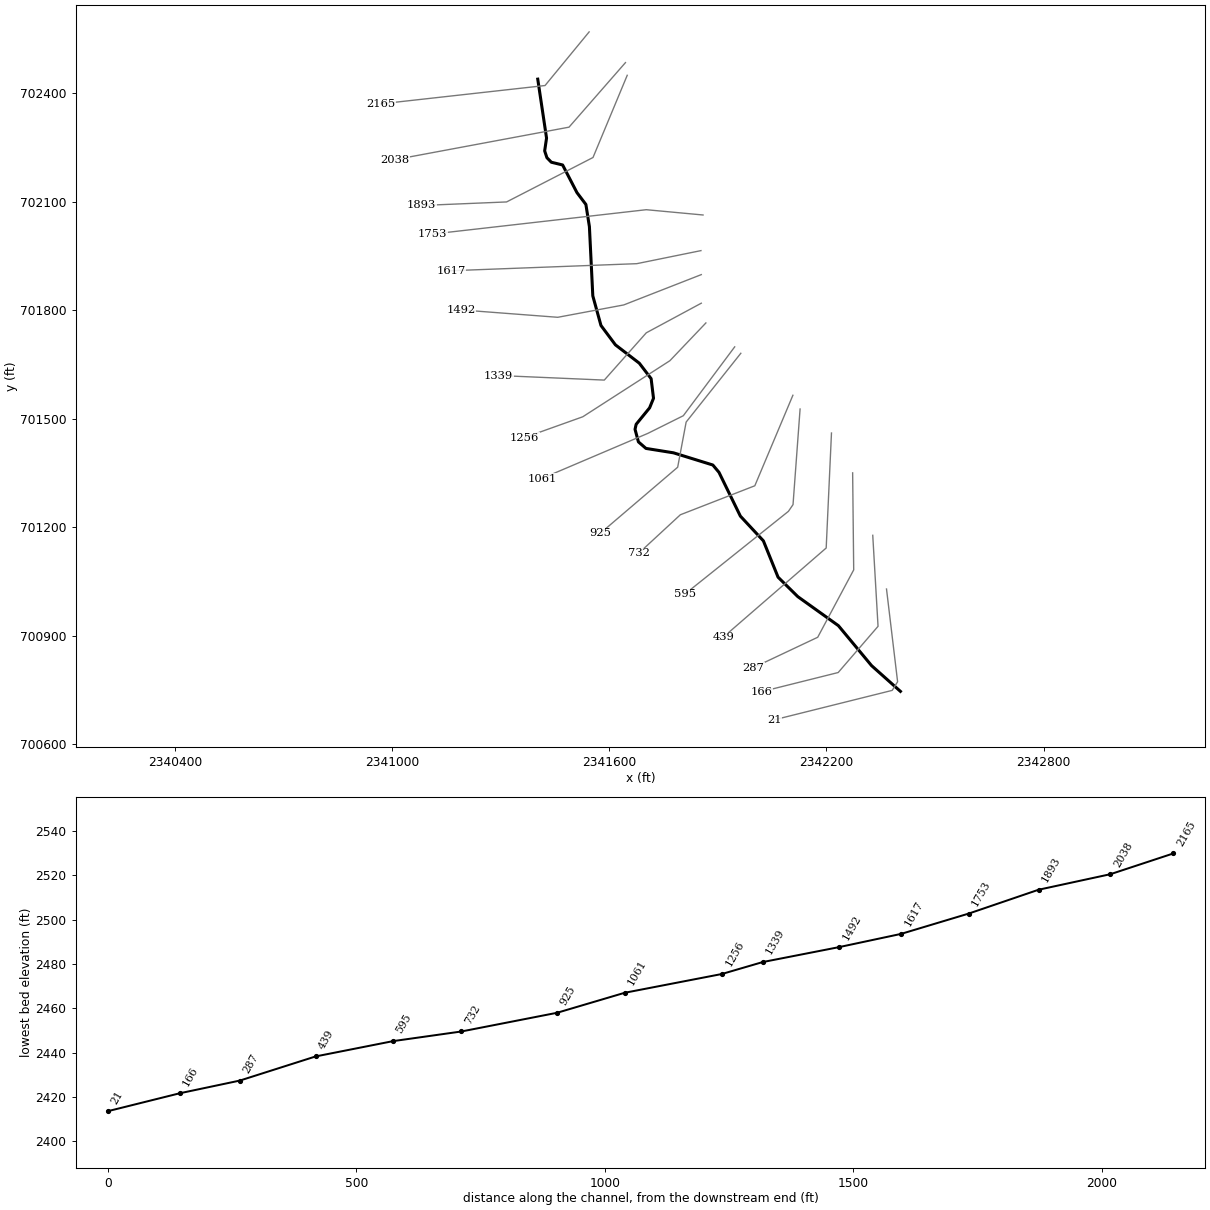
--- STALNAKRN3.prj (project) ---

Proj Title=STALNAKRN3
Current Plan=p01
Default Exp/Contr=0,0
English Units
Geom File=g01
Flow File=f01
Plan File=p01
BEGIN DESCRIPTION:
----------MODEL BY WOOD PLC 2022----------
AFH study
Randolph County, WV
HEC-RAS Version: RAS 6.2
Vertical Datum: NAVD88
Projection: NAD 1983 StatePlane West Virginia S FIPS 4702 (US Feet)
Terrain: 1-meter LIDAR (FEMA Region III 3DEP collected 2016-2018)
Land Use: 2019 NLCD
Hydrologic Method:
WV SIR2010-5033 regression equations
Additional Model Notes:
None
END DESCRIPTION:
DSS Export Rating Curves= 0
DSS Export Rating Curve Sorted= 0
DSS Export Volume Flow Curves= 0
DXF OffsetX= 0
DXF OffsetY= 0
DXF ScaleX= 0
DXF ScaleY= 0

--- STALNAKRN3.p01 (plan) ---

Plan Title=Floodplain
Program Version=6.20
Short Identifier=Floodplain
Geom File=g01
Flow File=f01
Subcritical Flow
K Sum by GR= 0
Std Step Tol= 0.01
Critical Tol= 0.01
Num of Std Step Trials= 20
Max Error Tol= 0.3
Flow Tol Ratio= 0.001
Split Flow NTrial= 30
Split Flow Tol= 0.02
Split Flow Ratio= 0.02
Log Output Level= 0
Friction Slope Method= 1
Unsteady Friction Slope Method= 2
Unsteady Bridges Friction Slope Method= 1
Parabolic Critical Depth
Global Vel Dist= 0 , 0 , 0
Global Log Level= 0
CheckData=True
Encroach Param=-1 ,0,0, 0
Mapping Interval=1HOUR
Computation Time Step Use Courant=        0
Computation Time Step Use Time Series=    0
Computation Time Step Count To Double=0
Computation Time Step Max Doubling=0
Computation Time Step Max Halving=0
Computation Time Step Residence Courant=0
Run HTab= 0
Run UNet= 0
Run Sediment= 0
Run PostProcess= 0
Run WQNet= 0
Run RASMapper=-1
UNET Theta= 0
UNET Theta Warmup= 0
UNET ZTol= 0
UNET ZSATol= 0
UNET MxIter= 0
UNET Max Iter WO Improvement= 0
UNET MaxInSteps= 0
UNET DtIC= 0
UNET DtMin= 0
UNET MaxCRTS= 0
UNET WFStab= 0
UNET SFStab= 0
UNET WFX= 1
UNET SFX= 1
UNET Gravity=32.174
UNET 1D Methodology=Finite Difference
UNET DSS MLevel= 1
UNET Pardiso=0
UNET DZMax Abort= 0
UNET Use Existing IB Tables= 0
UNET Froude Reduction=False
UNET Froude Limit= 0
UNET Froude Power= 0
UNET D1 Cores= 0
UNET WindReference=Eulerian
UNET WindDragFormulation=Hsu (1988)
UNET D2 Coriolis=0
UNET D2 Cores= 0
UNET D2 Theta= 1
UNET D2 Theta Warmup= 1
UNET D2 Z Tol= 0.01
UNET D2 Volume Tol= 0.01
UNET D2 Max Iterations= 20
UNET D2 Equation= 0
UNET D2 RampUpFraction=0.1
UNET D2 TimeSlices= 1
UNET D2 Turbulence Formulation=Non-Conservative (original)
UNET D2 Eddy Viscosity=0.3
UNET D2 Transverse Eddy Viscosity=0.1
UNET D2 Smagorinsky Mixing=0
UNET D2 BCVolumeCheck=0
UNET D2 Cores=0
UNET D2 SolverType=PARDISO (Direct)
UNET D2 Minimum Iterations= 2147483647
UNET D2 Maximum Iterations= 2147483647
UNET D2 Restart Number= 10
UNET D2 Relaxation Coeff=1.3
UNET D2 SOR Precondition Iterations= 10
UNET D2 ILUT Maximum Fill= 8
UNET D2 ILUT Tolerance=1E-08
UNET D1D2 MaxIter= 0
UNET D1D2 ZTol=0.01
UNET D1D2 QTol=0.1
UNET D1D2 MinQTol=1
Write IC File= 0
Write IC File at Fixed DateTime=0
Write IC File at Sim End=0
Echo Input=False
Echo Parameters=False
Echo Output=False
Write Detailed= 0
HDF Write Warmup=0
HDF Write Time Slices=0
HDF Flush=0
HDF Compression= 1
HDF Chunk Size= 1
HDF Spatial Parts= 1
HDF Use Max Rows=0
HDF Fixed Rows= 1
Calibration Method= 0
Calibration Iterations= 20
Calibration Max Change=0.05
Calibration Tolerance=0.2
Calibration Maximum=1.5
Calibration Minimum=0.5
Calibration Optimization Method= 1
WQ AD Non Conservative
WQ ULTIMATE=-1
WQ Max Comp Step=1HOUR
WQ Output Interval=15MIN
WQ Output Selected Increments= 0
WQ Output face flow=0
WQ Output face velocity=0
WQ Output face area=0
WQ Output face dispersion=0
WQ Output cell volume=0
WQ Output cell surface area=0
WQ Output cell continuity=0
WQ Output cumulative cell continuity=0
WQ Output face conc=0
WQ Output face dconc_dx=0
WQ Output face courant=0
WQ Output face peclet=0
WQ Output face adv mass=0
WQ Output face disp mass=0
WQ Output cell mass=0
WQ Output cell source sink temp=0
WQ Output nsm pathways=0
WQ Output nsm derived pathways=0
WQ Create Restart=0
WQ Fixed Restart=0
WQ System Summary=0
WQ Write To DSS=0
Sorting and Armoring Iterations= 10
XS Update Threshold= 0.02
Bed Roughness Predictor= 0
Hydraulics Update Threshold= 0.02
Energy Slope Method= 1
Volume Change Method= 1
Sediment Retention Method= 0
Sediment TS Multiplier= 1
Warm Up Method= 0
XS Weighting Method= 0
Number of US Weighted Cross Sections= 1
Number of DS Weighted Cross Sections= 1
Upstream XS Weight=0
Main XS Weight=1
Downstream XS Weight=0
Number of DS XS's Weighted with US Boundary= 1
Upstream Boundary Weight= 1
Weight of XSs Associated with US Boundary= 0
Number of US XS's Weighted with DS Boundary= 1
Downstream Boundary Weight= 0.5
Weight of XSs Associated with DS Boundary= 0.5
Percentile Method= 0
Sediment Output Level= 3
Mass or Volume Output= 0
Output Increment Type= 1
Profile and TS Output Increment= 1
Transport Output Increment 1
XS Output Flag= 0
XS Output Increment= 10
Read HDF5 Sediment Hotstart= 0
Sediment Hotstart Type= 0
Write Gradation File= 0
Read Gradation Hotstart= 0
Write HDF5 File= 1
Write Binary Output= 1
Write DSS Sediment File= 0
DSS Sediment Output Type= 1
SV Curve= 0
Specific Gage Flag= 0
Subcell Erosion Methods= 0
Subcell Deposition Methods= 0
Advection Scheme= 1
Matrix Solver= 0
Implicit Weighting Factor= 1
Maximum Outer Loop Convergence Iterations= 5
Convergence Maximum Absolute= 0.001
Convergence RMSE= 0.0001
Grain Fractions Max Abs Error= 0.001
Max Subgrid Regions= 1
Max Subgrid Length Scale= 3.402823E+38
Initial Layer Thickness= 3.402823E+38
Min Layer Thickness= 3.402823E+38
Max Layer Thickness= 3.402823E+38
Number of Layers= 5

--- STALNAKRN3.f01 (steady flow) ---

Flow Title=Flow
Program Version=4.00
Number of Profiles=1
Profile Names=P100yr
River Rch & RM=STALNAKRN3,Main,2165
     417
Boundary for River Rch & Prof#=STALNAKRN3,Main      ,1
Up Type=0
Dn Type=3
Dn Slope=0.054689

--- STALNAKRN3.g01 (geometry) ---

Geom Title=Geometry
Program Version=6.20

River Reach=STALNAKRN3      ,Main
Reach XY= 30
     2341402.609702438.0430000132341426.91500004702275.195999995
     2341421.707702239.7789999992341427.95600003702221.028999999
     2341440.109702208.5290000142341471.35900004702200.890000016
     2341510.943702124.5020000042341535.59499998 702091.86300002
2341545.31699999702030.4040000142341554.69200002701839.432000011
2341577.26200002701757.4880000052341617.19300002701704.015000016
2341683.16500001701653.3209999952341715.80400003 701610.61300002
2341722.40100002701556.4459999952341711.63699999701530.057000011
     2341674.484701484.5709999952341671.35900003701470.682000011
     2341680.734701435.960000008     2341701.567701417.903999999
2341777.60899998701405.7510000172341886.29000002 701372.07100001
2341903.30400003701351.7580000162341962.33100004701230.924999997
2342025.92816758701162.577167615     2342066.498701062.174999997
     2342120.925701008.5290000142342233.07800004700928.320999995
2342324.74500005700817.904000014 2342404.5333503700746.763397531

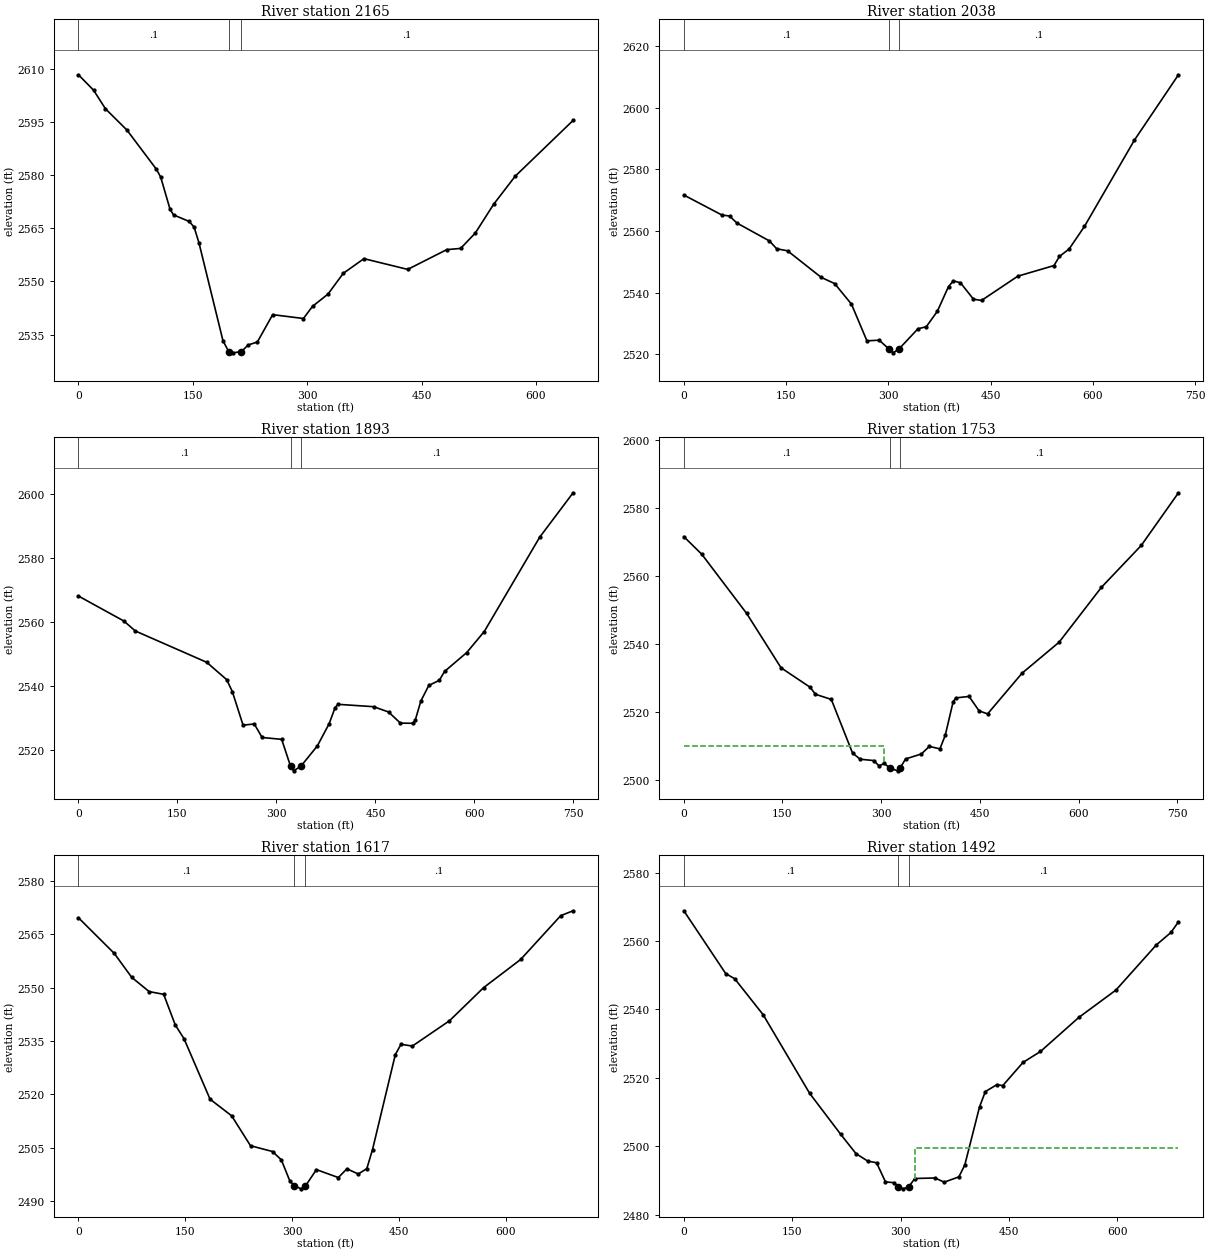
Type RM Length L Ch R = 1 ,2165    ,126.7,126.8,127.5
XS GIS Cut Line= 3
 2341544.5461041702568.5191723462341422.73255221702420.393893249
2340968.61163077702369.719455663
#Sta/Elev= 30
       0 2608.34    19.9 2603.97    35.4 2598.75    63.6 2592.73   102.1 2581.71
   107.8 2579.49   120.2 2570.32   124.8 2568.78   145.4 2566.93   151.7 2565.32
     158 2560.93   189.5  2533.3     197 2530.22   202.4 2529.86   213.7  2530.2
   222.5 2532.08   234.6 2532.91   254.7 2540.64     295 2539.55     307 2542.99
   327.2 2546.43   347.3  2552.3   374.4 2556.44   431.8 2553.41     483 2558.99
   501.2 2559.33   520.4 2563.66   544.5 2571.79   572.7  2579.7   648.7 2595.46
#Mann= 3, -1 ,  0
       0     0.1       0     197   0.045       0   213.7     0.1       0
Bank Sta=197,213.7
XS Rating Curve= 0 ,0
Exp/Cntr(USF)=0,0
Exp/Cntr=0.3,0.1

Type RM Length L Ch R = 1 ,2038    ,142.6,144.6,145.5
XS GIS Cut Line= 3
2341644.92047086702483.7369402322341488.99912444702305.401900266
2341008.56647579702215.747126076
#Sta/Elev= 30
       0 2571.64    55.8 2565.16    67.2 2564.82    77.8 2562.57   125.6 2556.75
   136.2 2554.22   152.2 2553.55   201.7 2544.92   221.2 2542.94   245.9 2536.28
   268.6 2524.37   286.6 2524.58  301.432521.635   306.9 2520.48   315.22521.634
   343.5 2528.28   355.7 2528.94     372 2533.98   388.3 2541.98   395.5  2543.8
   405.8  2543.2   424.9 2537.87   436.7 2537.46     490 2545.33     543 2548.77
     551 2551.72   565.2 2554.14   587.7 2561.45   660.9  2589.4   725.6 2610.61
#Mann= 3, -1 ,  0
       0     0.1       0  301.43   0.045       0   315.2     0.1       0
Bank Sta=301.43,315.2
XS Rating Curve= 0 ,0
Exp/Cntr(USF)=0,0
Exp/Cntr=0.3,0.1

Type RM Length L Ch R = 1 ,1893    ,143,140.4,137.1
XS GIS Cut Line= 4
2341649.79301293702448.6546372882341555.26569667702221.594176567
2341316.51113497702098.8061162632341081.65460693702089.061032112
#Sta/Elev= 30
       0 2568.02    68.8 2560.22    86.1 2557.12   194.4 2547.33   224.7  2541.9
   233.2 2538.16   249.4 2527.72   266.4 2528.09   278.3 2523.87   307.9 2523.29
   321.4  2514.9   325.9 2513.46   336.92514.867   361.9 2521.21   379.9  2528.2
   388.9 2533.22   393.4 2534.22   447.3 2533.48   469.8 2531.83   487.8 2528.36
     507  2528.3   510.3 2529.26   518.8 2535.24   530.8  2540.1   546.8 2541.72
   554.8  2544.5   588.3 2550.37   614.9 2556.95   698.9 2586.39   749.5 2600.25
#Mann= 3, -1 ,  0
       0     0.1       0   321.4   0.045       0   336.9     0.1       0
Bank Sta=321.4,336.9
XS Rating Curve= 0 ,0
Exp/Cntr(USF)=0,0
Exp/Cntr=0.3,0.1

Type RM Length L Ch R = 1 ,1753    ,136.6,136.1,135.4
XS GIS Cut Line= 3
2341859.31232218702062.7493049042341702.41646735702077.366931131
2341111.86436779702010.125850488
#Sta/Elev= 30
       0 2571.48    27.3 2566.31    95.5 2548.93   147.8 2532.97     192 2527.25
   200.1 2525.19   224.2 2523.68   256.5 2507.92   268.2 2506.12   288.7 2505.73
   296.7 2504.16   304.8 2504.89   312.8 2503.56   324.9 2502.71   328.9 2503.58
   337.1  2506.2   361.1 2507.66   373.2 2509.88   389.3 2509.16   397.4 2513.15
   409.4 2522.99   413.5 2524.13   433.6 2524.56   448.9 2520.31   461.8 2519.44
   514.1 2531.37   570.5 2540.49   634.9 2556.62   695.3 2568.88   751.9 2584.36
#Mann= 3, -1 ,  0
       0     0.1       0   312.8   0.045       0   328.9     0.1       0
#XS Ineff= 2 , 0
          304.98    2510
Permanent Ineff=
       F       F
Bank Sta=312.8,328.9
XS Rating Curve= 0 ,0
Exp/Cntr(USF)=0,0
Exp/Cntr=0.3,0.1

Type RM Length L Ch R = 1 ,1617    ,124.2,125,126.4
XS GIS Cut Line= 3
2341853.46527169701964.3239549782341676.10474014701928.267143619
2341162.53880538701908.776975317
#Sta/Elev= 30
       0 2569.56    50.3 2559.57    74.8 2552.85    99.3 2548.86   119.7 2548.09
     136  2539.5   148.3 2535.64   184.9 2518.67   215.2 2514.02   241.7 2505.63
   272.6 2504.01     285 2501.67     297 2495.73   303.5 2494.35     313 2493.54
   318.9 2494.35   334.3 2498.93   365.1  2496.7   377.1 2499.16   393.1  2497.7
   405.1 2499.21   413.1 2504.54   445.1 2531.16   453.1 2534.07   469.1 2533.58
   521.2 2540.67   569.2 2549.97   621.2 2557.86   677.5 2570.15   694.9 2571.52
#Mann= 3, -1 ,  0
       0     0.1       0   303.5   0.045       0   318.9     0.1       0
Bank Sta=303.5,318.9
XS Rating Curve= 0 ,0
Exp/Cntr(USF)=0,0
Exp/Cntr=0.3,0.1

Type RM Length L Ch R = 1 ,1492    ,148.8,153.3,157.9
XS GIS Cut Line= 4
2341854.43978011 701898.057382752341640.04792878701814.249659051
2341457.81485516701780.141864522  2341189.825041701800.606541239
#Sta/Elev= 30
       0 2568.86      58 2550.49    70.4 2548.99   109.8 2538.46   174.2 2515.45
   217.2 2503.47   238.2 2497.86   254.5 2495.67   266.7 2495.19     279  2489.6
   291.1 2489.35  296.432488.152   303.3 2487.56  311.132488.113   319.6 2490.58
   347.5 2490.74   360.3 2489.51   380.6 2491.06   388.8 2494.55   409.2 2511.55
   417.2 2515.99   433.3 2518.04   441.3 2517.74   469.4 2524.53   493.5 2527.72
   546.5 2537.67   597.8 2545.66   653.9  2558.9     674 2562.51   684.4 2565.63
#Mann= 3, -1 ,  0
       0     0.1       0  296.43   0.045       0  311.13     0.1       0
#XS Ineff= 2 , 0
                          320.08         2499.36
Permanent Ineff=
       F       F
Bank Sta=296.43,311.13
XS Rating Curve= 0 ,0
Exp/Cntr(USF)=0,0
Exp/Cntr=0.3,0.1

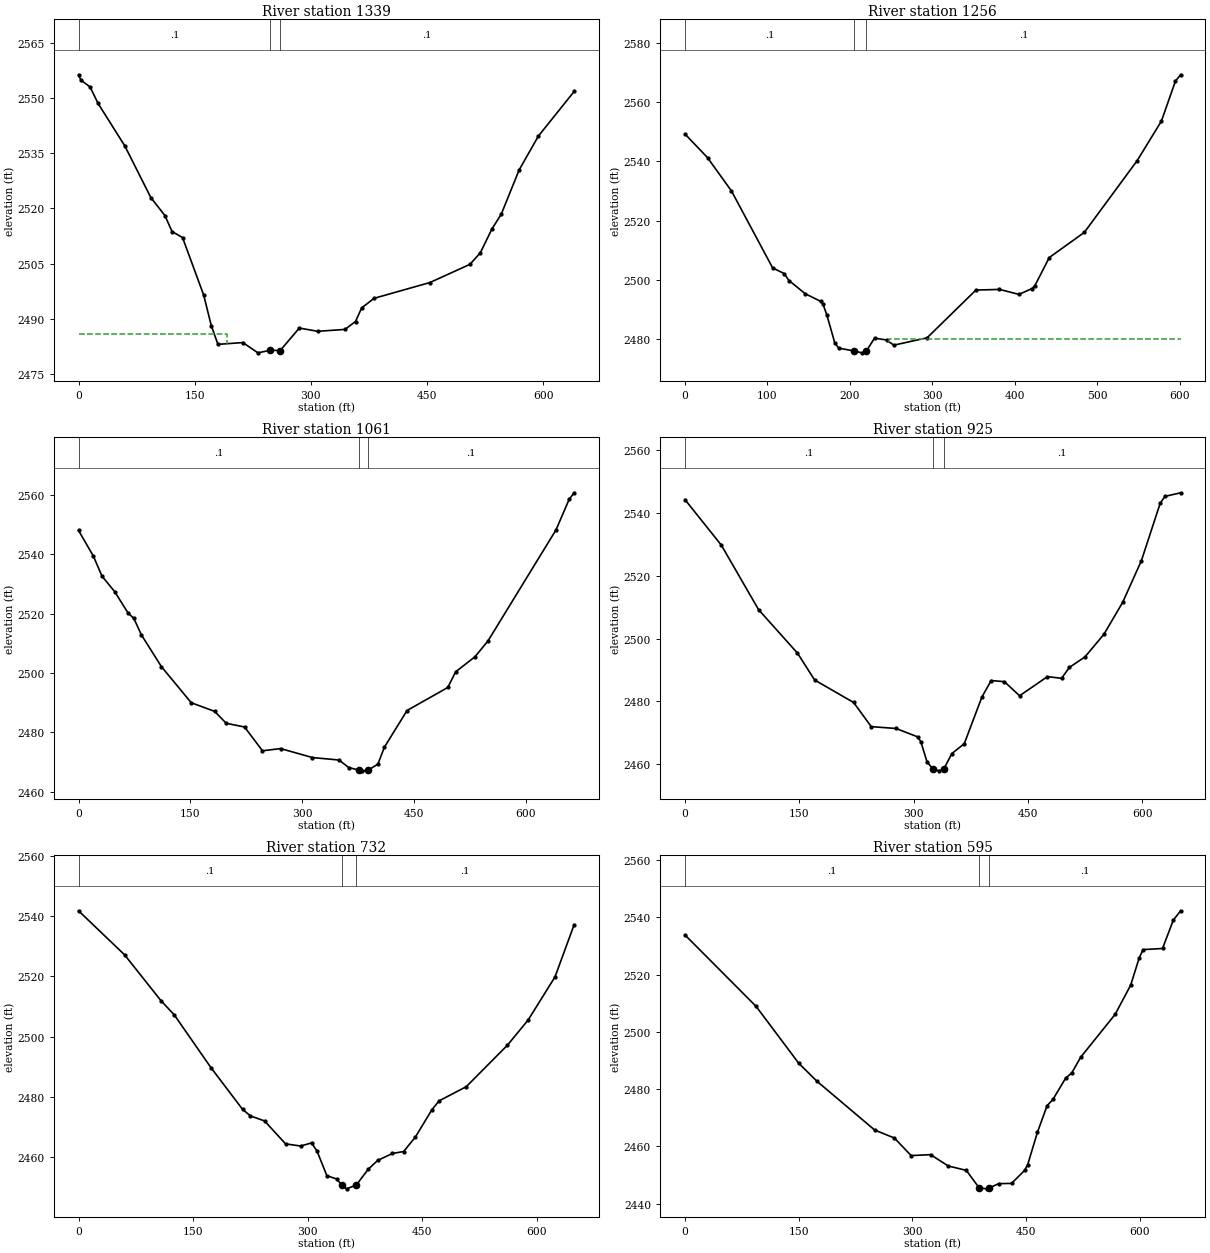
Type RM Length L Ch R = 1 ,1339    ,84.4,82.2,80.3
XS GIS Cut Line= 4
2341854.43978011701819.1222011262341702.41646735701737.263494257
2341586.44996595701606.6793666322341294.09744142701619.347976029
#Sta/Elev= 30
       0 2556.25     3.1 2554.79    14.9 2552.96    25.3 2548.46    59.9 2536.91
    93.4 2522.93   111.6 2518.06   120.7 2513.74   134.3  2512.1   161.6  2496.5
   171.4 2488.22     180 2483.13   212.2 2483.62   231.6 2480.83   247.7 2481.53
   260.4 2481.46   285.1 2487.56   308.6 2486.67     344 2487.18   357.6 2489.33
   365.6 2493.02   381.6 2495.62   453.7  2499.9   505.4 2504.84   518.7 2507.95
   533.8 2514.46   545.8 2518.45   568.9 2530.46   593.8 2539.65   639.9 2551.73
#Mann= 3, -1 ,  0
       0     0.1       0   247.7   0.045       0   260.4     0.1       0
#XS Ineff= 2 , 0
          191.22 2485.87
Permanent Ineff=
       F       F
Bank Sta=247.7,260.4
XS Rating Curve= 0 ,0
Exp/Cntr(USF)=0,0
Exp/Cntr=0.3,0.1

Type RM Length L Ch R = 1 ,1256    ,200,195.4,195.3
XS GIS Cut Line= 4
 2341867.1083895 701764.549729882341767.70853116701660.277329464
2341527.00495263701505.3304914612341366.21106414701447.834494969
#Sta/Elev= 30
       0  2549.2    27.4 2541.21    56.4 2529.99   106.3 2504.07   120.2 2502.17
   126.1 2499.82     146 2495.33   164.6 2492.79   167.3 2491.89     172 2488.26
   181.6 2478.88   186.3 2477.05   205.3 2476.05   214.9 2475.44  219.962476.041
   229.9  2480.4   244.4 2479.77   253.2 2478.03   293.6  2480.5   352.8 2496.59
   381.4 2496.82   405.1 2495.14   420.9 2497.11   424.2 2498.01   441.8 2507.56
   484.3 2516.04   548.4 2540.23   577.8 2553.56   594.8 2567.04   601.1 2569.16
#Mann= 3, -1 ,  0
       0     0.1       0   205.3   0.045       0  219.96     0.1       0
#XS Ineff= 2 , 0
                          247.79         2480.26
Permanent Ineff=
       F       F
Bank Sta=205.3,219.96
XS Rating Curve= 0 ,0
Exp/Cntr(USF)=0,0
Exp/Cntr=0.3,0.1

Type RM Length L Ch R = 1 ,1061    ,132.3,135.9,144
XS GIS Cut Line= 4
2341946.66989271701698.4794446032341804.73985094701508.254016706
2341706.87389902701459.5257678852341413.83210729701334.771990187
#Sta/Elev= 30
       0 2548.06    19.9 2539.41    31.6 2532.61    48.4 2527.45    66.5 2520.21
    74.2 2518.41    84.4 2512.83   111.3  2502.1   151.3 2489.94   182.8 2487.01
   198.2 2483.01   222.8 2481.76   246.9 2473.73   271.2 2474.48   313.9 2471.45
   349.6 2470.62   362.6 2468.09  376.772467.192     381 2466.97   388.7 2467.21
   401.8 2469.24   410.5 2474.94   440.9 2487.32   495.6 2495.08   506.1 2500.36
   532.2 2505.47   549.6 2510.81   640.9 2548.26   658.5 2558.57   665.2 2560.75
#Mann= 3, -1 ,  0
       0     0.1       0  376.77   0.045       0   388.7     0.1       0
Bank Sta=376.77,388.7
XS Rating Curve= 0 ,0
Exp/Cntr=0.3,0.1

Type RM Length L Ch R = 1 ,925     ,198.2,192.7,181.6
XS GIS Cut Line= 4
 2341963.5847226701680.7420061812341812.53591826701490.712865234
 2341789.1477163  701365.97578812341575.73037339701183.742714475
#Sta/Elev= 30
       0 2544.18    47.7 2529.71    96.5 2509.22   147.6 2495.38   170.1 2486.83
   221.3 2479.68   244.4    2472   276.9 2471.42   305.4 2468.74   309.5 2467.17
   317.6 2460.79   325.7 2458.41   333.8 2457.95   339.4 2458.45   350.1 2463.44
   366.4 2466.56   389.4 2481.32   401.7 2486.66   419.1  2486.3     439 2481.82
   475.6 2487.91   494.1 2487.37   504.3 2490.82   524.9  2494.2   549.7 2501.38
   574.2  2511.5   598.8 2524.76   623.4 2542.97   629.6  2545.2   650.3 2546.36
#Mann= 3, -1 ,  0
       0     0.1       0   325.7   0.045       0   339.4     0.1       0
Bank Sta=325.7,339.4
XS Rating Curve= 0 ,0
Exp/Cntr(USF)=0,0
Exp/Cntr=0.3,0.1

Type RM Length L Ch R = 1 ,732     ,136.3,137.2,142.2
XS GIS Cut Line= 4
2342107.43464216701564.7363525022342002.25598156 701314.73102922
 2341796.5418865701234.6205080712341681.56620035701128.322971712
#Sta/Elev= 30
       0 2541.72    60.3 2527.11     108 2511.88   125.4 2507.17   173.4 2489.66
   214.7 2475.86     225 2473.68   243.5 2472.02   270.9 2464.42   290.6  2463.7
   304.9 2464.73   312.1 2462.04     325 2453.85   337.9 2452.77  344.182450.814
   350.7  2449.5   363.6 2450.78   363.6 2450.79   379.1    2456   391.4 2458.91
   410.8 2461.24   425.4 2461.87   440.9  2466.7   462.3 2475.68   471.8 2478.67
   507.4 2483.38   561.2 2497.12   588.4  2505.5   623.5 2519.78   648.6 2537.12
#Mann= 3, -1 ,  0
       0     0.1       0  344.18   0.045       0   363.6     0.1       0
Bank Sta=344.18,363.6
XS Rating Curve= 0 ,0
Exp/Cntr=0.3,0.1

Type RM Length L Ch R = 1 ,595     ,155.4,155.8,155
XS GIS Cut Line= 4
2342127.30213634701526.7696765932342107.81196804701262.677896099
2342095.14335864701244.162236212 2341808.6378846701015.152758661
#Sta/Elev= 30
       0 2533.84    93.8  2508.9   149.9 2489.09   174.1 2482.75   250.3  2465.7
   276.3 2462.91   298.4 2456.78   324.1  2457.1   347.4 2453.14   371.2 2451.61
   388.1 2445.52   398.6 2445.16   400.9 2445.42   413.9 2446.97   430.9 2447.06
     448 2451.57   452.2 2453.59     465 2464.88   477.8  2474.2   485.6 2476.43
   502.1 2483.74   510.6 2485.75     522 2491.09   567.6 2506.11   588.1 2516.32
   599.5 2525.95   604.5 2528.72   630.1 2529.11   644.4 2539.04     654 2542.28
#Mann= 3, -1 ,  0
       0     0.1       0   388.1   0.045       0   400.9     0.1       0
Bank Sta=388.1,400.9
XS Rating Curve= 0 ,0
Exp/Cntr(USF)=0,0
Exp/Cntr=0.3,0.1

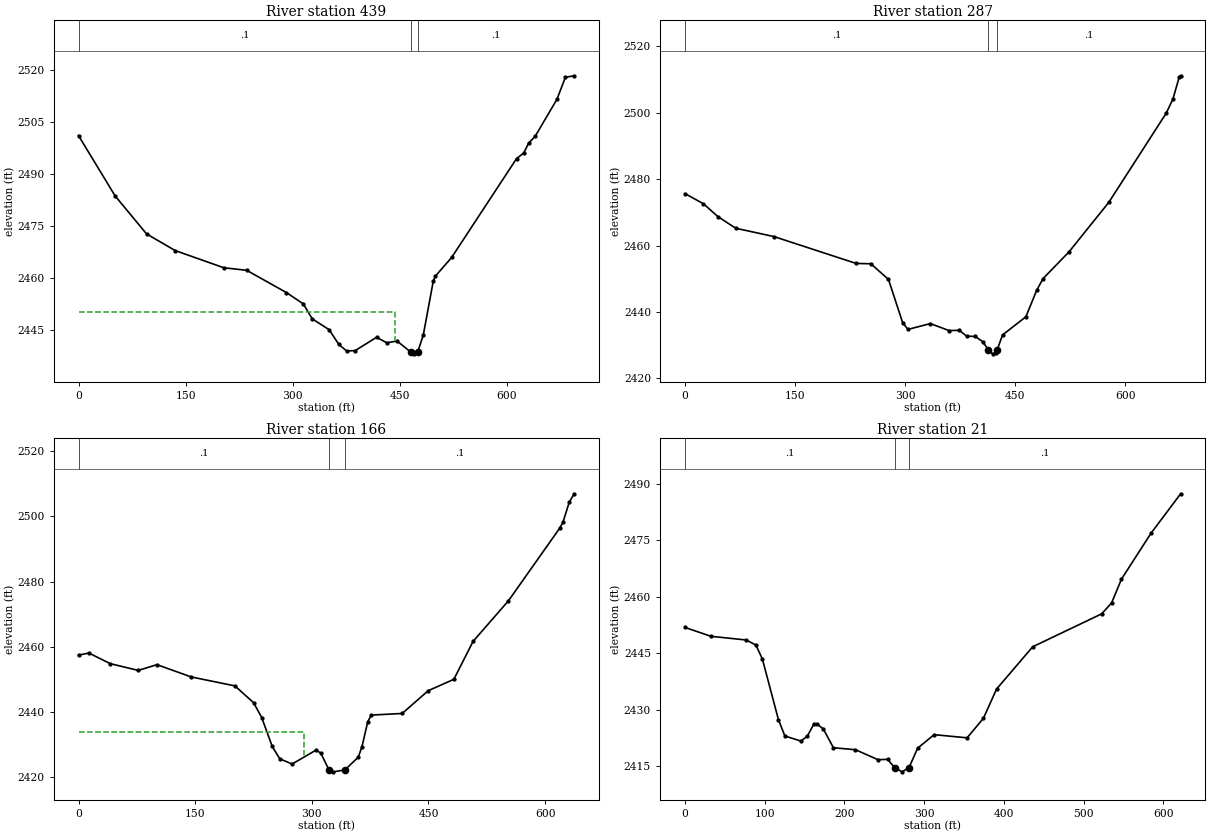
Type RM Length L Ch R = 1 ,439     ,150.9,152.6,155
XS GIS Cut Line= 3
2342214.03338528701460.5031043662342199.41575906 701142.81336104
2341914.85930184700896.262732017
#Sta/Elev= 30
       0  2501.1    51.4  2483.7    95.4 2472.78   135.5 2467.99   203.5 2463.05
   235.6 2462.31   291.2 2455.91     315 2452.63   327.6 2448.31   351.1 2445.22
   364.7 2440.98   375.5 2439.09   387.7 2439.18   417.6 2443.01   432.1 2441.43
   446.3 2441.94   465.2 2438.81   470.5 2438.25  475.332438.815   483.1 2443.67
     497  2459.1   500.1 2460.64   522.8    2466   613.7 2494.46     624 2496.12
   630.6  2498.9   639.9 2500.91   670.3 2511.53   682.2 2517.89   694.5 2518.33
#Mann= 3, -1 ,  0
       0     0.1       0   465.2   0.045       0  475.33     0.1       0
#XS Ineff= 2 , 0
          443.78 2450.33
Permanent Ineff=
       F       F
Bank Sta=465.2,475.33
XS Rating Curve= 0 ,0
Exp/Cntr(USF)=0,0
Exp/Cntr=0.3,0.1

Type RM Length L Ch R = 1 ,287     ,121.4,120.9,119.3
XS GIS Cut Line= 4
2342272.50389019701350.3836534592342275.42741544701082.393839303
2342176.02755709700896.2627320172341998.66702554700812.455008318
#Sta/Elev= 30
       0 2475.65    25.2 2472.58    45.2 2468.66    69.2 2465.21   121.2  2462.7
   233.2  2454.6   253.2  2454.5   277.2 2449.79   296.6  2436.7   303.8 2434.72
   334.3 2436.47   359.8 2434.36   373.7 2434.45   383.6  2432.7   395.5 2432.58
   405.4 2431.04   413.2 2428.62   419.1 2427.35   423.6 2427.72  425.422428.637
   432.6 2433.04   464.4 2438.53     479 2446.45   487.7 2450.01   523.1 2458.08
   577.4 2473.03   655.5 2499.88   664.7 2504.16   673.5 2510.94   675.2 2511.17
#Mann= 3, -1 ,  0
       0     0.1       0   413.2   0.045       0  425.42     0.1       0
Bank Sta=413.2,425.42
XS Rating Curve= 0 ,0
Exp/Cntr(USF)=0,0
Exp/Cntr=0.3,0.1

Type RM Length L Ch R = 1 ,166     ,143.2,144.9,145.7
XS GIS Cut Line= 4
2342328.05086985701177.8956639842342342.66849608700926.472492886
2342232.54904517700798.8118905062342022.05522751 700746.18843609
#Sta/Elev= 30
       0 2457.43    13.4 2458.07    40.8 2454.82    76.8 2452.75   100.9 2454.51
     145 2450.74   201.1    2448   225.1 2442.85   235.6 2438.29   249.1 2429.43
   258.8 2425.62   274.7 2424.02   305.6 2428.31   311.7 2427.32   322.2 2422.16
   327.5 2421.62   342.5 2422.19   359.8 2426.14   364.5 2429.33     372 2437.03
   376.5 2439.04   416.2 2439.53   449.7 2446.52   482.7 2450.01   507.4 2461.66
   552.8 2474.08   618.7 2496.36   622.9 2498.15   631.1 2504.38   637.4 2506.95
#Mann= 3, -1 ,  0
       0     0.1       0   322.2   0.045       0   342.5     0.1       0
#XS Ineff= 2 , 0
           289.6 2433.97
Permanent Ineff=
       F       F
Bank Sta=322.2,342.5
XS Rating Curve= 0 ,0
Exp/Cntr(USF)=0,0
Exp/Cntr=0.3,0.1

Type RM Length L Ch R = 1 ,21      ,,,
XS GIS Cut Line= 4
2342366.04684664701029.5461528532342396.71526066700773.334742023
2342381.80970044700749.5131833852342056.16302204700668.227762881
#Sta/Elev= 30
       0 2451.86    32.6  2449.5    76.9 2448.52      89 2447.17    97.1 2443.47
   117.2 2427.41   125.3 2423.04   145.4 2421.69   153.4 2422.96   161.5 2426.13
   165.5 2426.25   173.6 2424.88   186.2 2419.92   213.9 2419.39   242.1 2416.75
   254.2 2416.83263.22112414.601   272.4 2413.52  281.03 2414.63   291.9 2419.81
   312.6 2423.39   353.9 2422.55   374.4 2427.73   390.9  2435.5   436.2 2446.72
   522.8 2455.47   535.2 2458.37   547.6 2464.69   584.7 2476.88   621.8 2487.34
#Mann= 3, -1 ,  0
       0     0.1       0263.2211   0.045       0  281.03     0.1       0
Bank Sta=263.2211,281.03
XS Rating Curve= 0 ,0
Exp/Cntr(USF)=0,0
Exp/Cntr=0.3,0.1
LCMann Table=0

Chan Stop Cuts=-1
Use User Specified Reach Order=0
Composite Channel Slope=5